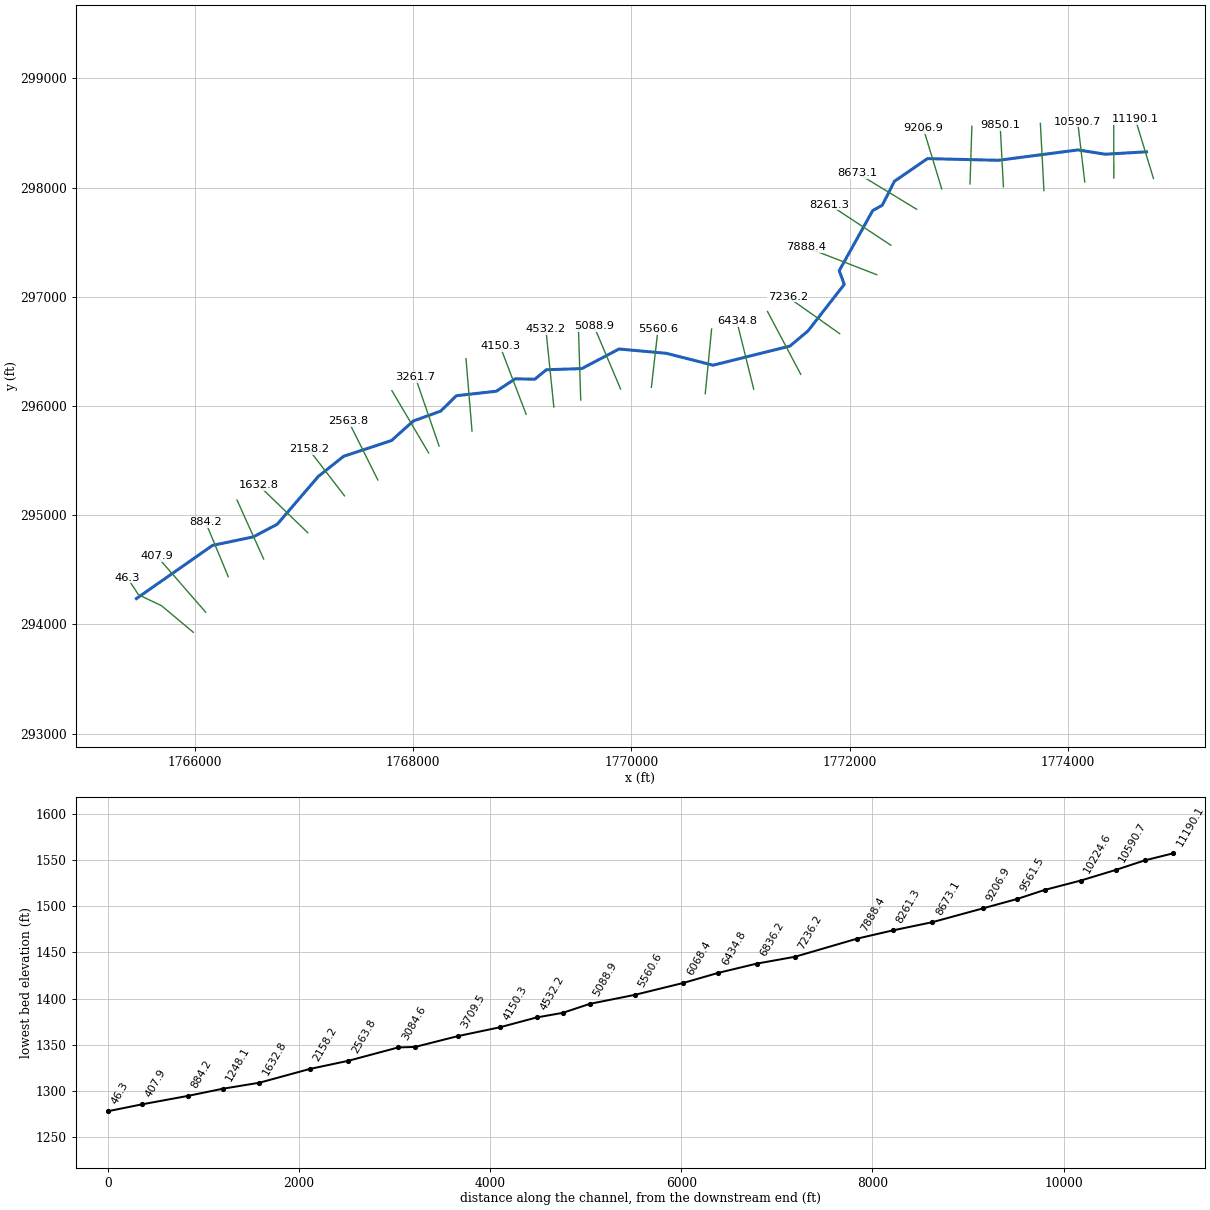
--- TONEYFRK.prj (project) ---

Proj Title=TONEYFRK
Current Plan=p01
Default Exp/Contr=0,0
English Units
Geom File=g01
Flow File=f01
Plan File=p01
BEGIN DESCRIPTION:
END DESCRIPTION:
DSS Export Rating Curves= 0
DSS Export Rating Curve Sorted= 0
DSS Export Volume Flow Curves= 0
DXF OffsetX= 0
DXF OffsetY= 0
DXF ScaleX= 0
DXF ScaleY= 0

--- TONEYFRK.p01 (plan) ---

Plan Title=Floodplain
Program Version=4.00
Geom File=g01
Flow File=f01
K Sum by GR=0
Std Step Tol=0.01
Critical Tol=0.01
Num of Std Step Trials=20
Max Error Tol=0.3
Flow Tol Ratio=0.001
Split Flow NTrial=30
Split Flow Tol=0.02
Split Flow Ratio=0.02
Log Output Level=0
Friction Slope Method=1
Unsteady Friction Slope Method=2
Unsteady Bridges Friction Slope Method=1
Global Log Level=0
CheckData=False
Run HTab=0
Run UNet=0
Run PostProcess=0
UNET Theta=0
UNET Theta Warmup=0
UNET ZTol=0
UNET ZSATol=0
UNET MxIter=0
UNET MaxInSteps=0
UNET DtIC=0
UNET DtMin=0
UNET MaxCRTS=0
UNET WFStab=0
UNET SFStab=0
UNET WFX=0
UNET SFX=0
UNET DSS MLevel=0
UNET DZMax Abort=0
UNET Convert EG Bridges=0
UNET Use Existing IB Tables=0
UNET Froude Limit=0
UNET Froude Power=0
Write IC File=0
Echo Input=False
Echo Output=False
Write Detailed=0

--- TONEYFRK.f01 (steady flow) ---

Flow Title=NFF Regression Equation
Program Version=4.00
Number of Profiles=1
Profile Names=P100yr
River Rch & RM=TONEYFRK,Main      ,11190.1
903.6022
River Rch & RM=TONEYFRK,Main      ,8673.1
959.2291
River Rch & RM=TONEYFRK,Main      ,8261.3
1106.844
River Rch & RM=TONEYFRK,Main      ,6434.8
1175.838
River Rch & RM=TONEYFRK,Main      ,3261.7
1305.820
River Rch & RM=TONEYFRK,Main      ,46.3
1448.790
Boundary for River Rch & Prof#=TONEYFRK,Main      ,1
Up Type=0
Dn Type=3
Dn Slope=0.019729

--- TONEYFRK.g01 (geometry) ---

Geom Title=USGS 10m DEM
Program Version=4.10

River Reach=TONEYFRK        ,Main
Reach XY= 30
     1774719.324      298327.722     1774340.591      298305.716
     1774091.578      298345.095     1773363.068      298250.122
     1772712.028      298265.503     1772409.867       298057.86
     1772297.875      297838.569     1772210.437      297789.518
     1771903.732      297239.011      1771950.06      297113.925
     1771617.656      296687.706     1771452.033      296548.722
     1770747.845      296373.833     1770318.152      296482.704
     1769886.142      296522.083     1769544.472      296342.561
     1769220.175      296332.138     1769113.621      296245.272
     1768934.677      296249.166     1768761.056      296135.364
     1768395.331      296094.385     1768251.917      295953.405
     1768000.633       295862.69     1767800.218      295683.544
     1767362.418      295539.927     1767129.619      295354.614
     1766753.473      294917.099     1766534.623      294801.838
     1766160.203      294723.393     1765462.964      294236.576

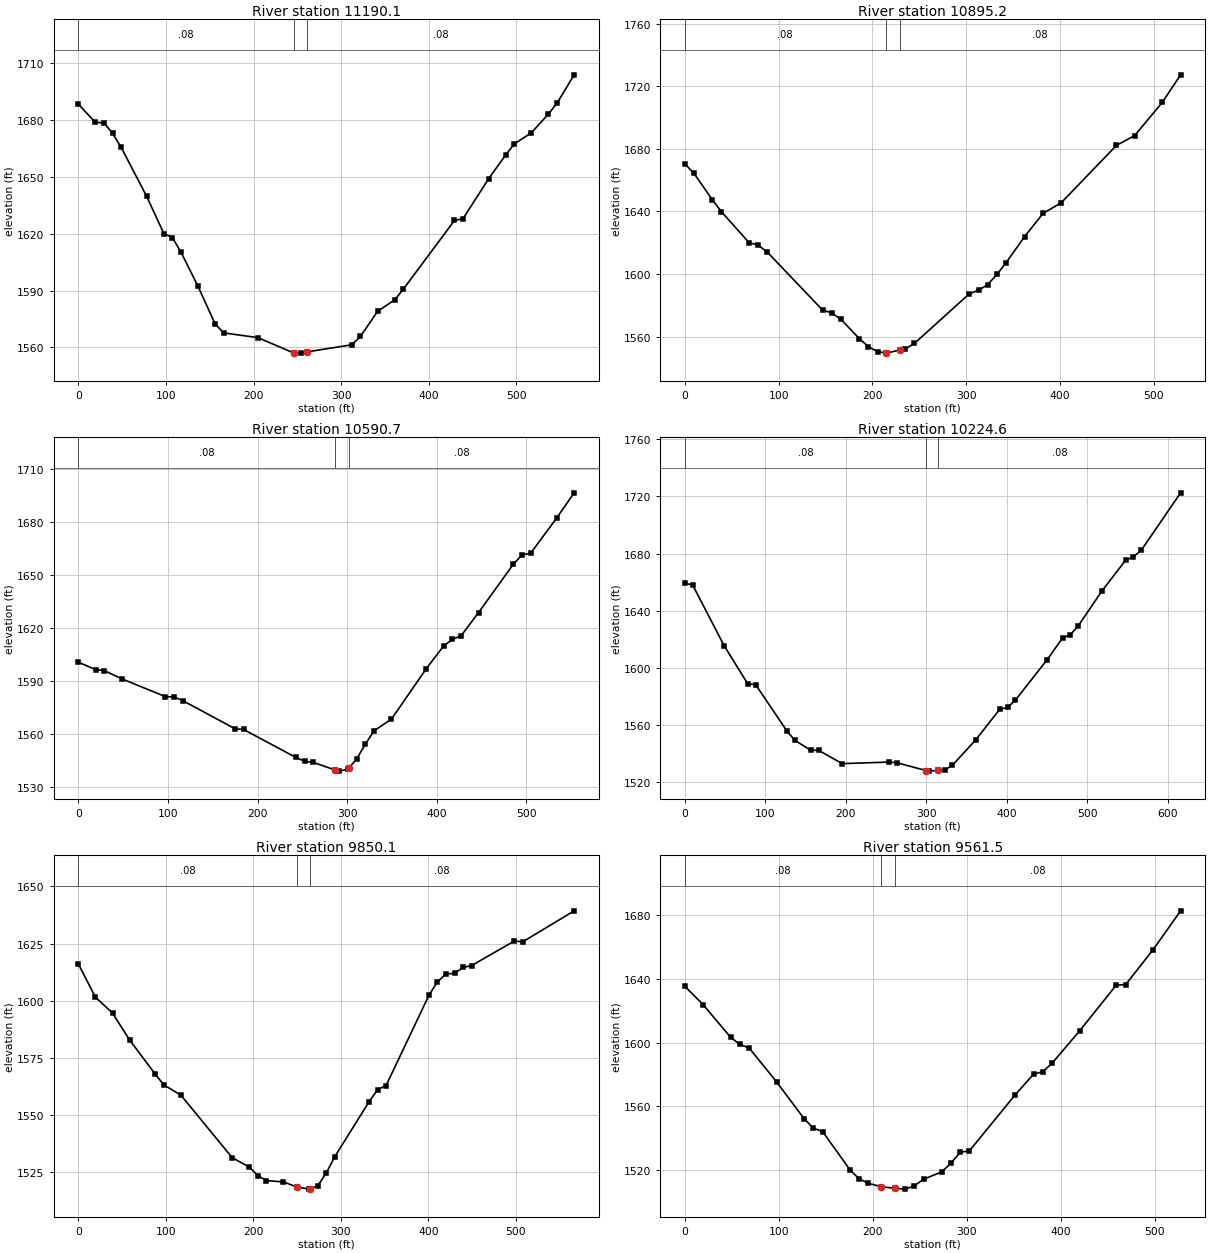
Type RM Length L Ch R = 1 ,11190.1 ,301.6,294.9,288.2
XS GIS Cut Line= 2
     1774783.446      298083.233     1774618.407      298624.434
#Sta/Elev= 30
       0 1688.25    19.5 1678.59    29.3 1678.46      39 1672.86    48.8 1665.55
      78 1639.61    97.6 1620.04   107.3 1617.91   117.1 1610.28   136.6 1592.22
   156.1 1572.42   165.8  1567.7   204.9  1565.2   245.7 1557.12   253.6 1557.03
   260.7 1557.68   312.2 1561.43   321.9  1565.8   341.4 1579.02     361 1585.12
   370.7 1590.64   429.2 1626.94     439 1627.87   468.2 1648.96   487.8 1661.55
   497.5  1667.3     517 1673.16   536.5 1683.08   546.3 1688.78   565.8  1703.7
#Mann= 3 , 0 , 0
       0     .08       0   245.7    .045       0   260.7     .08       0
Bank Sta=245.7,260.7
XS Rating Curve= 0 ,0
Exp/Cntr=0.3,0.1

Type RM Length L Ch R = 1 ,10895.2 ,301.7,304.5,307.2
XS GIS Cut Line= 2
     1774420.125       298087.61     1774419.311      298616.061
#Sta/Elev= 30
       0 1670.49     9.8 1664.35    29.4 1647.47    39.1 1639.82    68.5 1620.07
    78.3 1618.47    88.1 1613.92   146.8 1577.02   156.6 1575.17   166.4 1571.03
   185.9 1558.79   195.7 1553.56   205.5 1550.42   214.2 1549.57   215.3 1549.46
   229.2 1551.54   234.9 1552.08   244.6 1555.62   303.4 1587.51   313.2  1589.7
   322.9  1593.3   332.7 1599.85   342.5 1607.35   362.1 1623.94   381.7 1638.74
   401.2  1645.6     460 1682.25   479.5 1688.58   508.9  1709.8   528.4 1727.37
#Mann= 3 , 0 , 0
       0     .08       0   214.2    .045       0   229.2     .08       0
Bank Sta=214.2,229.2
XS Rating Curve= 0 ,0
Exp/Cntr=0.3,0.1

Type RM Length L Ch R = 1 ,10590.7 ,367.6,366.1,364.7
XS GIS Cut Line= 2
     1774153.695      298052.719     1774089.114      298602.174
#Sta/Elev= 30
       0 1600.65    19.4 1596.46    29.1 1595.89    48.5 1591.28    97.1 1581.22
   106.8    1581   116.5 1578.95   174.7 1563.07   184.4 1562.63   242.6 1546.87
   252.4 1544.67   262.1 1544.02   286.9 1539.69   291.2  1539.1   300.9 1540.25
   301.9 1540.86   310.6 1546.07   320.3 1554.38     330 1561.92   349.4 1568.54
   388.2 1596.99   407.6 1609.87   417.4 1613.56   427.1 1615.61   446.5  1628.7
   485.3 1656.02     495  1661.3   504.7 1662.28   533.8 1682.22   553.2 1696.39
#Mann= 3 , 0 , 0
       0     .08       0   286.9    .045       0   301.9     .08       0
Bank Sta=286.9,301.9
XS Rating Curve= 0 ,0
Exp/Cntr=0.3,0.1

Type RM Length L Ch R = 1 ,10224.6 ,374.7,374.5,374.4
XS GIS Cut Line= 2
      1773779.77      297972.806     1773747.043      298587.788
#Sta/Elev= 30
       0  1659.3     9.8 1657.92    48.9 1615.42    78.2 1588.75      88  1588.2
   127.1  1555.5   136.9 1549.13   156.4 1542.25   166.2  1542.2   195.5 1532.89
   254.2 1533.98   263.9 1533.43     300 1527.99     303 1527.63     315  1528.2
   322.6  1528.3   332.4 1531.77   361.7 1549.76     391 1570.84   400.8 1572.23
   410.6 1577.36   449.7 1605.39   469.2 1620.87     479 1623.25   488.8  1629.5
   518.1 1653.81   547.4 1675.26   557.2 1677.68     567 1682.38   615.8 1722.52
#Mann= 3 , 0 , 0
       0     .08       0     300    .045       0     315     .08       0
Bank Sta=300,315
XS Rating Curve= 0 ,0
Exp/Cntr=0.3,0.1

Type RM Length L Ch R = 1 ,9850.1  ,290.3,288.6,286.9
XS GIS Cut Line= 2
     1773408.555      298006.553     1773378.449      298572.286
#Sta/Elev= 30
       0 1616.12    19.5 1601.58    39.1 1594.58    58.6 1582.81    87.9 1567.87
    97.7 1563.21   117.2 1558.68   175.8 1531.35   195.4 1527.21   205.1 1523.51
   214.9 1521.33   234.4 1520.73   249.4 1518.56   263.7 1517.59   264.4 1517.69
   273.5 1519.02   283.3 1524.65     293  1531.8   332.1 1555.75   341.9 1561.12
   351.6  1562.9   400.5  1602.3   410.2 1608.25     420 1611.71   429.8 1611.96
   439.6 1614.54   449.3 1615.37   498.2 1626.11   507.9 1625.78   566.5 1639.32
#Mann= 3 , 0 , 0
       0     .08       0   249.4    .045       0   264.4     .08       0
Bank Sta=249.4,264.4
XS Rating Curve= 0 ,0
Exp/Cntr=0.3,0.1

Type RM Length L Ch R = 1 ,9561.5  ,347.2,354.6,362
XS GIS Cut Line= 2
     1773102.213      298034.402     1773119.465      298561.394
#Sta/Elev= 30
       0 1635.41    19.5 1623.84    48.8 1603.27    58.6 1598.79    68.4 1596.62
    97.6 1575.28   126.9 1552.08   136.7 1546.15   146.5 1544.05   175.8 1519.84
   185.5 1514.21   195.3 1511.46   208.6 1509.36   223.6 1508.29   234.3  1507.8
   244.1 1509.91   253.9 1513.96   273.4 1518.73   283.2 1524.22   292.9 1530.98
   302.7 1531.89   351.5 1567.23     371 1580.16   380.8 1581.69   390.6    1587
   419.9 1607.37   458.9 1636.18   468.7 1636.37     498 1658.39   527.3 1682.87
#Mann= 3 , 0 , 0
       0     .08       0   208.6    .045       0   223.6     .08       0
Bank Sta=208.6,223.6
XS Rating Curve= 0 ,0
Exp/Cntr=0.3,0.1

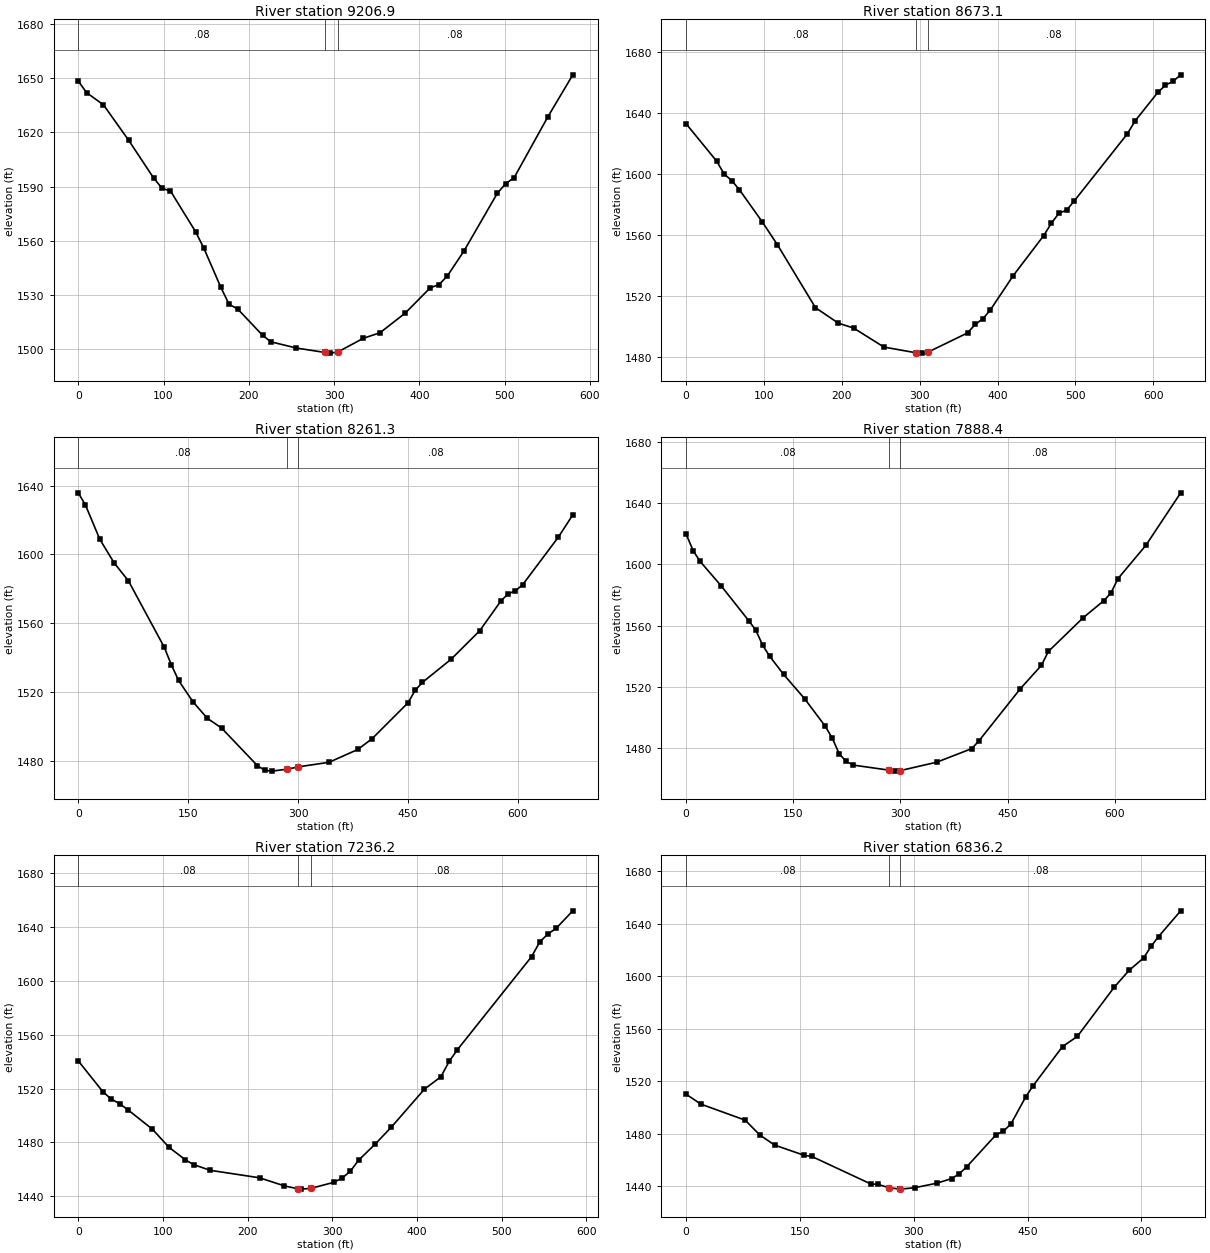
Type RM Length L Ch R = 1 ,9206.9  ,517,533.8,550.6
XS GIS Cut Line= 2
     1772842.999      297987.927      1772674.25       298542.67
#Sta/Elev= 30
       0  1648.4     9.8 1641.98    29.5 1635.28      59 1615.69    88.4 1594.69
    98.3    1589   108.1 1587.54   137.6 1564.92   147.4 1555.69   167.1  1534.2
   176.9 1524.71   186.7 1522.26   216.2 1507.54     226 1503.96   255.5 1500.57
     289  1498.1   294.8 1497.72     304 1498.29   334.2 1505.93   353.8 1509.03
   383.3 1519.88   412.8 1533.98   422.6 1535.59   432.4 1540.25   452.1 1554.21
   491.4 1586.35   501.2 1591.63     511  1594.9   550.4 1628.51   579.8 1651.88
#Mann= 3 , 0 , 0
       0     .08       0     289    .045       0     304     .08       0
Bank Sta=289,304
XS Rating Curve= 0 ,0
Exp/Cntr=0.3,0.1

Type RM Length L Ch R = 1 ,8673.1  ,411.6,411.7,411.8
XS GIS Cut Line= 2
     1772613.593      297801.509      1772070.76      298131.488
#Sta/Elev= 30
       0 1632.73    39.1 1608.36    48.9 1599.84    58.6 1595.56    68.4 1589.62
    97.7 1568.64   117.3 1553.57   166.1 1512.44   195.5 1502.29     215 1499.13
   254.1 1486.65   295.3 1482.92     303 1482.69   310.3 1483.25   361.6 1495.93
   371.4 1501.56   381.2 1505.12   390.9 1511.02   420.2 1533.42   459.3 1559.56
   469.1 1567.63   478.9 1574.24   488.7 1576.19   498.4 1582.17   566.8 1626.18
   576.6 1634.52   605.9 1653.27   615.7 1657.98   625.5 1660.54   635.3 1664.78
#Mann= 3 , 0 , 0
       0     .08       0   295.3    .045       0   310.3     .08       0
Bank Sta=295.3,310.3
XS Rating Curve= 0 ,0
Exp/Cntr=0.3,0.1

Type RM Length L Ch R = 1 ,8261.3  ,368.2,373,377.7
XS GIS Cut Line= 2
     1772376.405      297472.959     1771813.156      297844.376
#Sta/Elev= 30
       0 1635.81     9.8 1628.71    29.3 1608.84    48.9 1595.05    68.4 1584.61
   117.3 1545.95   127.1  1535.6   136.9  1526.6   156.4 1514.22     176 1504.61
   195.6 1498.88   244.4 1477.02   254.2 1474.39     264 1473.84     285 1474.97
     300 1476.31   342.2 1478.99   381.3 1486.43   400.9 1492.73   449.8 1513.57
   459.6 1520.82   469.4 1525.44   508.5  1538.9   547.6  1555.5   576.9 1573.05
   586.7 1577.08   596.5  1578.8   606.2 1582.28   655.1  1610.1   674.7 1623.02
#Mann= 3 , 0 , 0
       0     .08       0     285    .045       0     300     .08       0
Bank Sta=285,300
XS Rating Curve= 0 ,0
Exp/Cntr=0.3,0.1

Type RM Length L Ch R = 1 ,7888.4  ,657.7,652.2,646.6
XS GIS Cut Line= 2
      1772248.15       297202.26      1771602.64      297452.619
#Sta/Elev= 30
       0  1619.7     9.8 1608.95    19.5 1601.95    48.8 1586.08    87.8 1563.09
    97.5    1557   107.3 1547.04     117  1539.9   136.5  1528.1   165.8 1512.28
     195 1494.11   204.8 1486.27   214.5 1476.08   224.3  1471.3     234 1468.89
   283.9  1465.6   292.6 1464.95   298.9  1465.2   351.1 1470.82   399.8 1479.64
   409.6 1484.52   468.1 1518.88   497.3 1533.97   507.1 1543.09   555.8  1565.1
   585.1 1576.38   594.8 1581.33   604.6 1590.68   643.6 1612.38   692.4  1646.7
#Mann= 3 , 0 , 0
       0     .08       0   283.9    .045       0   298.9     .08       0
Bank Sta=283.9,298.9
XS Rating Curve= 0 ,0
Exp/Cntr=0.3,0.1

Type RM Length L Ch R = 1 ,7236.2  ,410.6,400,389.4
XS GIS Cut Line= 2
     1771907.621      296662.588      1771430.68      296999.791
#Sta/Elev= 30
       0 1540.59    29.2 1517.56    38.9 1512.25    48.7 1508.83    58.4 1504.37
    87.6 1489.82   107.1 1476.41   126.6 1467.05   136.3  1463.5   155.8  1459.3
   214.2 1453.72   243.4 1447.72   259.6 1445.55   262.8 1445.31   274.6 1445.86
   301.8 1450.35   311.5 1453.46   321.3 1458.55     331 1466.73   350.5 1478.63
   369.9 1491.45   408.9 1519.61   428.3 1528.79   438.1 1540.26   447.8 1548.91
   535.4 1618.04   545.2 1629.08   554.9 1634.94   564.6 1639.18   584.1 1652.08
#Mann= 3 , 0 , 0
       0     .08       0   259.6    .045       0   274.6     .08       0
Bank Sta=259.6,274.6
XS Rating Curve= 0 ,0
Exp/Cntr=0.3,0.1

Type RM Length L Ch R = 1 ,6836.2  ,406.9,401.5,396
XS GIS Cut Line= 2
     1771550.969      296290.219      1771246.07      296866.147
#Sta/Elev= 30
       0  1510.1    19.4 1502.58    77.8 1490.38    97.3 1478.97   116.7 1471.39
   155.6 1463.62   165.4 1462.82   243.2 1441.87   252.9 1441.48   267.3 1438.99
   282.1  1437.9   282.3 1437.91   301.5    1439   330.7 1442.46   350.1 1445.96
   359.9 1449.57   369.6  1454.8   408.5 1479.35   418.2 1482.07     428 1487.46
   447.4 1508.01   457.1 1516.48     496 1546.39   515.5 1554.09   564.1 1591.55
   583.6 1604.29     603 1613.92   612.8 1622.76   622.5 1630.07   651.7 1649.67
#Mann= 3 , 0 , 0
       0     .08       0   267.3    .045       0   282.3     .08       0
Bank Sta=267.3,282.3
XS Rating Curve= 0 ,0
Exp/Cntr=0.3,0.1

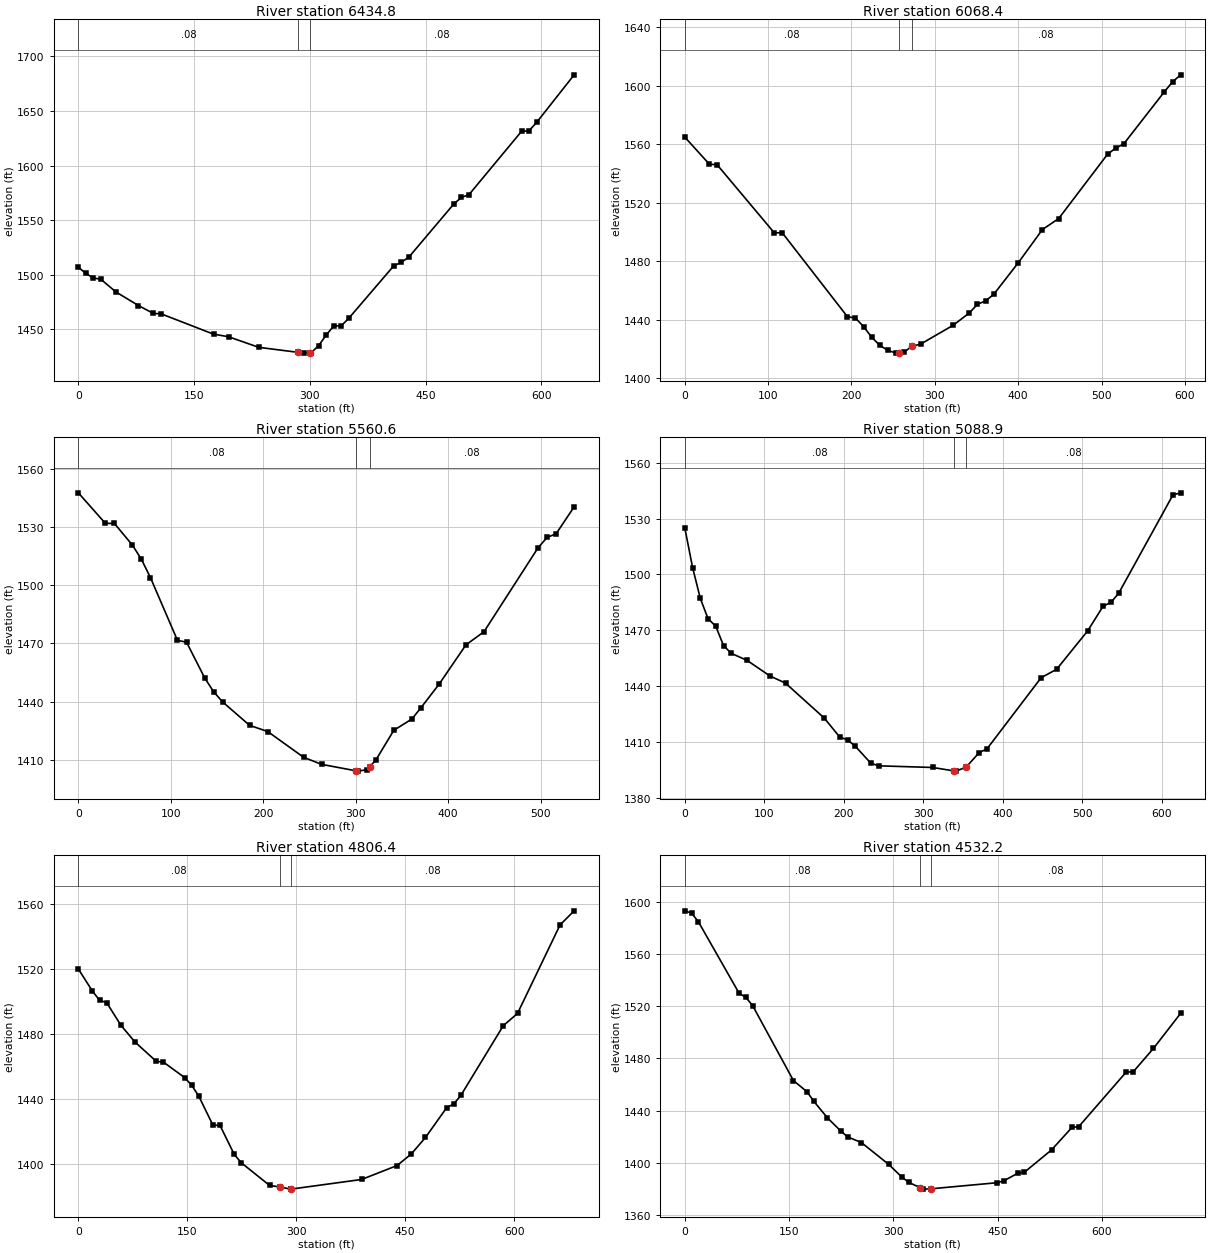
Type RM Length L Ch R = 1 ,6434.8  ,373.6,366.3,359
XS GIS Cut Line= 2
     1771120.181      296154.036     1770965.068      296777.612
#Sta/Elev= 30
       0 1506.79     9.7 1501.02    19.5 1496.88    29.2 1495.66    48.7 1484.06
    77.9 1471.59    97.4  1464.3   107.1 1464.03   175.2 1445.35   194.7 1442.96
   233.7 1433.28   285.2 1428.61   292.1 1427.94   300.2 1428.27   301.8 1428.34
   311.6 1434.93   321.3 1444.61     331 1452.85   340.8 1453.04   350.5 1459.88
   408.9  1508.1   418.6 1511.18   428.4    1516   486.8 1564.88   496.5 1570.77
   506.3 1573.29   574.4 1631.35   584.2 1631.92   593.9 1639.51   642.6 1683.19
#Mann= 3 , 0 , 0
       0     .08       0   285.2    .045       0   300.2     .08       0
Bank Sta=285.2,300.2
XS Rating Curve= 0 ,0
Exp/Cntr=0.3,0.1

Type RM Length L Ch R = 1 ,6068.4  ,508.2,507.8,507.5
XS GIS Cut Line= 2
     1770675.975      296112.833     1770734.289      296704.901
#Sta/Elev= 30
       0 1564.81    29.3 1546.42      39 1545.77   107.3 1499.38     117 1499.33
   195.1 1441.96   204.8 1441.04   214.6 1435.08   224.3 1427.92   234.1 1422.25
   243.8 1418.88   253.6 1417.03   257.3 1417.32   263.3 1417.78   272.3 1421.67
   282.8 1423.16   321.8 1436.02   341.4 1444.52   351.1 1450.45   360.9 1452.77
   370.6 1457.21   399.9  1478.7   429.1  1501.6   448.6  1509.1   507.2 1553.09
   516.9 1557.26   526.7 1560.21   575.4 1595.85   585.2 1602.62   594.9 1607.44
#Mann= 3 , 0 , 0
       0     .08       0   257.3    .045       0   272.3     .08       0
Bank Sta=257.3,272.3
XS Rating Curve= 0 ,0
Exp/Cntr=0.3,0.1

Type RM Length L Ch R = 1 ,5560.6  ,460.1,471.7,483.4
XS GIS Cut Line= 2
     1770182.168      296171.297       1770243.2      296704.052
#Sta/Elev= 30
       0 1547.49    29.2 1531.78      39 1531.71    58.5 1520.56    68.2 1513.27
      78 1503.81   107.2  1471.5     117 1470.58   136.5 1452.29   146.2 1445.11
     156 1439.81   185.2 1427.73   204.8 1424.54   243.7 1411.25   263.2 1407.62
   300.1 1404.33   302.2 1404.15     312 1404.85   315.1 1406.44   321.7 1409.82
   341.2  1425.2   360.7 1430.97   370.5 1436.78     390 1448.84   419.2  1469.2
   438.7 1475.95   497.2 1519.22     507 1524.55   516.7 1526.39   536.2  1540.3
#Mann= 3 , 0 , 0
       0     .08       0   300.1    .045       0   315.1     .08       0
Bank Sta=300.1,315.1
XS Rating Curve= 0 ,0
Exp/Cntr=0.3,0.1

Type RM Length L Ch R = 1 ,5088.9  ,290.8,282.5,274.1
XS GIS Cut Line= 2
     1769900.032      296156.094     1769656.341      296730.329
#Sta/Elev= 30
       0 1524.97     9.8  1503.7    19.5 1487.13    29.2 1476.27      39 1472.13
    48.7 1461.81    58.5 1457.59      78 1453.92   107.2 1445.46   126.7 1441.63
   175.4 1422.89   194.9  1412.7   204.7 1411.17   214.4  1407.8   233.9  1398.7
   243.7 1397.24   311.9 1396.35   338.9 1394.49   341.1 1394.39   353.9 1396.51
   370.4 1404.36   380.1 1406.29   448.4 1444.58   467.8 1449.06   506.8 1469.65
   526.3 1482.94   536.1 1484.95   545.8 1489.82   614.1 1542.64   623.8 1543.79
#Mann= 3 , 0 , 0
       0     .08       0   338.9    .045       0   353.9     .08       0
Bank Sta=338.9,353.9
XS Rating Curve= 0 ,0
Exp/Cntr=0.3,0.1

Type RM Length L Ch R = 1 ,4806.4  ,272.6,274.2,275.8
XS GIS Cut Line= 2
      1769534.92      296054.424     1769513.269      296736.735
#Sta/Elev= 30
       0 1519.89    19.5 1506.25    29.3 1500.63      39 1499.25    58.5 1485.39
      78 1475.05   107.3 1463.16     117 1462.75   146.3 1453.22     156 1448.51
   165.8 1441.81   185.3 1423.96     195 1423.86   214.6 1406.06   224.3  1400.9
   263.3 1386.97   277.1 1386.06   292.1 1384.71   292.6  1384.7   390.1 1390.64
   438.8 1399.18   458.4 1406.29   477.9 1416.41   507.1 1434.73   516.9 1437.03
   526.6 1442.24   585.1 1485.12   604.6 1492.59   663.2 1546.98   682.6 1555.61
#Mann= 3 , 0 , 0
       0     .08       0   277.1    .045       0   292.1     .08       0
Bank Sta=277.1,292.1
XS Rating Curve= 0 ,0
Exp/Cntr=0.3,0.1

Type RM Length L Ch R = 1 ,4532.2  ,375.2,381.9,388.6
XS GIS Cut Line= 2
     1769288.369      295991.353     1769215.709      296700.943
#Sta/Elev= 30
       0 1593.35     9.8 1591.56    19.5 1585.01    78.2 1530.01    87.9 1526.92
    97.7 1520.47   156.3 1463.02   175.9 1454.41   185.6 1447.12   205.2 1434.42
   224.7 1424.13   234.5 1419.74     254 1415.48   293.1 1398.77   312.7 1388.74
   322.4 1384.83   338.6  1380.8     342 1379.69   353.6 1379.92   449.5 1384.62
   459.2 1386.13   478.8 1391.83   488.6 1392.68   527.6  1409.8     557 1427.08
   566.7 1427.63   635.1 1469.64   644.9 1469.63   674.2 1487.72   713.3 1514.63
#Mann= 3 , 0 , 0
       0     .08       0   338.6    .045       0   353.6     .08       0
Bank Sta=338.6,353.6
XS Rating Curve= 0 ,0
Exp/Cntr=0.3,0.1

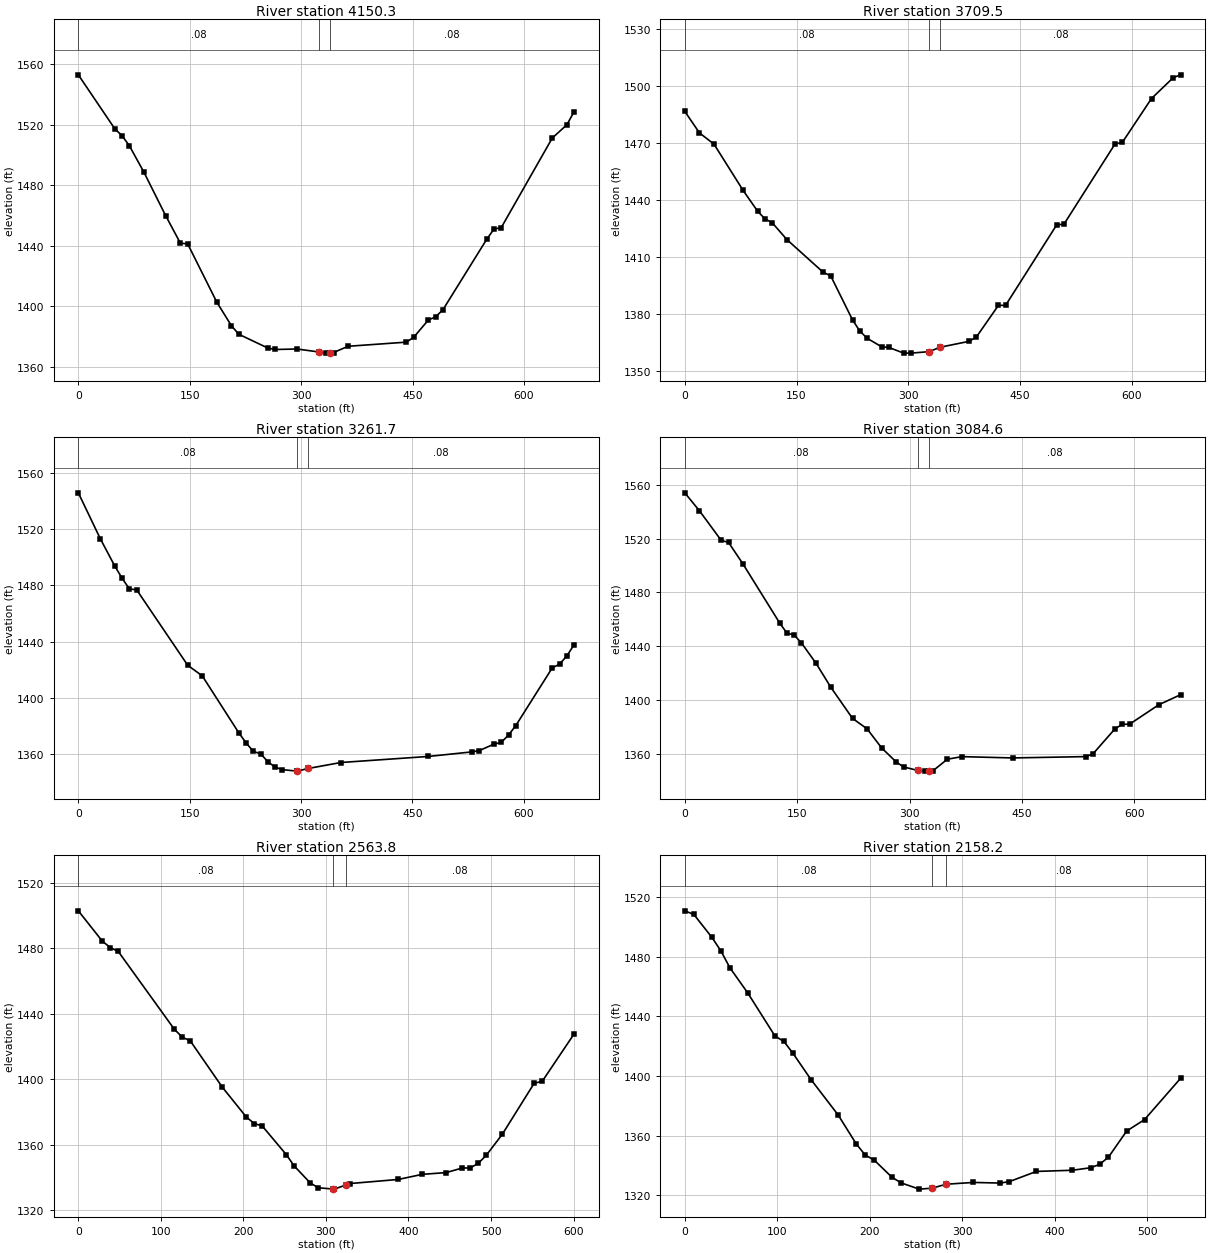
Type RM Length L Ch R = 1 ,4150.3  ,447.1,440.9,434.6
XS GIS Cut Line= 2
     1769034.312      295924.527     1768795.916      296548.019
#Sta/Elev= 30
       0 1553.04    49.1 1517.37    58.9 1512.78    68.7 1506.18    88.4 1488.59
   117.8 1459.76   137.4 1441.79   147.2 1441.34   186.5 1402.75   206.1 1387.24
     216 1381.62   255.2 1372.48     265 1371.54   294.5 1371.87   323.8  1369.9
   333.8 1369.14   338.8 1369.35   343.6 1369.55   363.2 1373.67   441.7  1376.4
   451.6 1379.67   471.2 1391.04     481 1393.13   490.8 1397.78   549.7 1444.31
   559.5 1451.09   569.4 1452.13   638.1 1511.31   657.7 1520.05   667.5 1528.78
#Mann= 3 , 0 , 0
       0     .08       0   323.8    .045       0   338.8     .08       0
Bank Sta=323.8,338.8
XS Rating Curve= 0 ,0
Exp/Cntr=0.3,0.1

Type RM Length L Ch R = 1 ,3709.5  ,442.2,447.8,453.1
XS GIS Cut Line= 2
     1768538.479      295770.756     1768483.455      296434.194
#Sta/Elev= 30
       0 1486.63    19.6 1475.32    39.2  1469.4    78.3 1445.07    97.9 1434.08
   107.7 1430.11   117.5 1428.02   137.1 1419.23     186 1401.98   195.8 1400.24
   225.2 1377.01     235 1371.16   244.8 1367.38   264.3 1362.87   274.1 1362.53
   293.7 1359.59   303.5 1359.56   327.9 1360.33   342.9 1362.67   381.8 1365.76
   391.6  1368.1     421 1384.62   430.8 1384.72   499.3 1426.96   509.1 1427.34
   577.6 1469.48   587.4 1470.28   626.6 1493.37   655.9 1504.37   665.7 1505.82
#Mann= 3 , 0 , 0
       0     .08       0   327.9    .045       0   342.9     .08       0
Bank Sta=327.9,342.9
XS Rating Curve= 0 ,0
Exp/Cntr=0.3,0.1

Type RM Length L Ch R = 1 ,3261.7  ,172.5,177.1,181.7
XS GIS Cut Line= 2
     1768236.778      295633.822     1768018.904      296264.964
#Sta/Elev= 30
       0 1545.86    29.5  1513.3    49.1 1493.74    58.9 1485.12    68.7 1477.55
    78.6 1476.82   147.3 1423.18   166.9 1415.64     216  1375.2   225.8 1368.04
   235.7 1361.85   245.5 1360.26   255.3 1354.48   265.1 1350.68   274.9 1348.91
   294.6 1347.87   294.7 1347.88   309.7 1349.77   353.5    1354   471.3 1358.31
   530.2 1361.56     540 1362.47   559.7 1367.09   569.5 1368.28   579.3 1373.53
   589.1 1380.26   638.2 1421.32     648 1423.93   657.9 1429.87   667.7 1437.84
#Mann= 3 , 0 , 0
       0     .08       0   294.7    .045       0   309.7     .08       0
Bank Sta=294.7,309.7
XS Rating Curve= 0 ,0
Exp/Cntr=0.3,0.1

Type RM Length L Ch R = 1 ,3084.6  ,522.4,520.9,519.3
XS GIS Cut Line= 2
      1768140.93       295570.65     1767804.561      296140.352
#Sta/Elev= 30
       0 1553.94    19.5 1540.64    48.6 1518.62    58.4  1517.1    77.8 1500.97
   126.5 1457.36   136.2 1449.83   145.9 1448.37   155.7 1442.44   175.1 1427.38
   194.6 1409.77   223.8 1386.45   243.2 1378.71   262.7  1364.5   282.2 1354.05
   291.9 1350.42   310.9 1347.81   321.1  1347.3   325.9 1347.35   330.8  1347.4
   350.3 1356.14   369.7 1358.05   437.8  1357.1   535.1 1358.08   544.8 1360.21
     574 1378.71   583.8 1382.07   593.5 1382.15   632.4 1396.56   661.6 1404.06
#Mann= 3 , 0 , 0
       0     .08       0   310.9    .045       0   325.9     .08       0
Bank Sta=310.9,325.9
XS Rating Curve= 0 ,0
Exp/Cntr=0.3,0.1

Type RM Length L Ch R = 1 ,2563.8  ,400.9,405.6,410.2
XS GIS Cut Line= 2
     1767675.606      295322.551     1767406.949      295859.866
#Sta/Elev= 30
       0 1502.83    29.1 1484.29    38.8 1480.37    48.4 1478.01   116.3 1430.51
     126 1425.67   135.6 1423.44   174.4 1395.18   203.5 1376.92   213.2 1372.93
   222.8 1371.46   251.9 1353.99   261.6    1347     281 1336.66   290.7 1333.73
   308.7 1332.94   310.1  1332.9   323.7 1335.36   329.4 1336.32   387.6 1338.81
   416.6 1341.92   445.7    1343   465.1  1345.8   474.8 1345.83   484.5 1348.66
   494.2 1353.54   513.5 1366.28   552.3 1397.57     562 1398.72   600.7 1427.73
#Mann= 3 , 0 , 0
       0     .08       0   308.7    .045       0   323.7     .08       0
Bank Sta=308.7,323.7
XS Rating Curve= 0 ,0
Exp/Cntr=0.3,0.1

Type RM Length L Ch R = 1 ,2158.2  ,522.1,525.4,528.7
XS GIS Cut Line= 2
     1767369.683        295177.9     1767042.661      295602.888
#Sta/Elev= 30
       0 1510.91     9.8 1508.47    29.2 1493.18      39 1484.02    48.8 1472.65
    68.2 1455.65    97.5 1426.83   107.2 1423.19     117 1415.21   136.5 1397.56
   165.8 1373.84   185.2 1354.59     195 1346.94   204.8 1343.51   224.2  1331.9
     234 1328.19   253.5 1324.01   267.5 1324.64   282.5  1327.3     312  1328.5
   341.2 1328.08     351 1329.06   380.2  1335.9   419.2 1336.69   438.8 1338.37
   448.5 1340.59   458.2 1345.51   477.8 1362.99   497.2 1370.72   536.2 1398.46
#Mann= 3 , 0 , 0
       0     .08       0   267.5    .045       0   282.5     .08       0
Bank Sta=267.5,282.5
XS Rating Curve= 0 ,0
Exp/Cntr=0.3,0.1

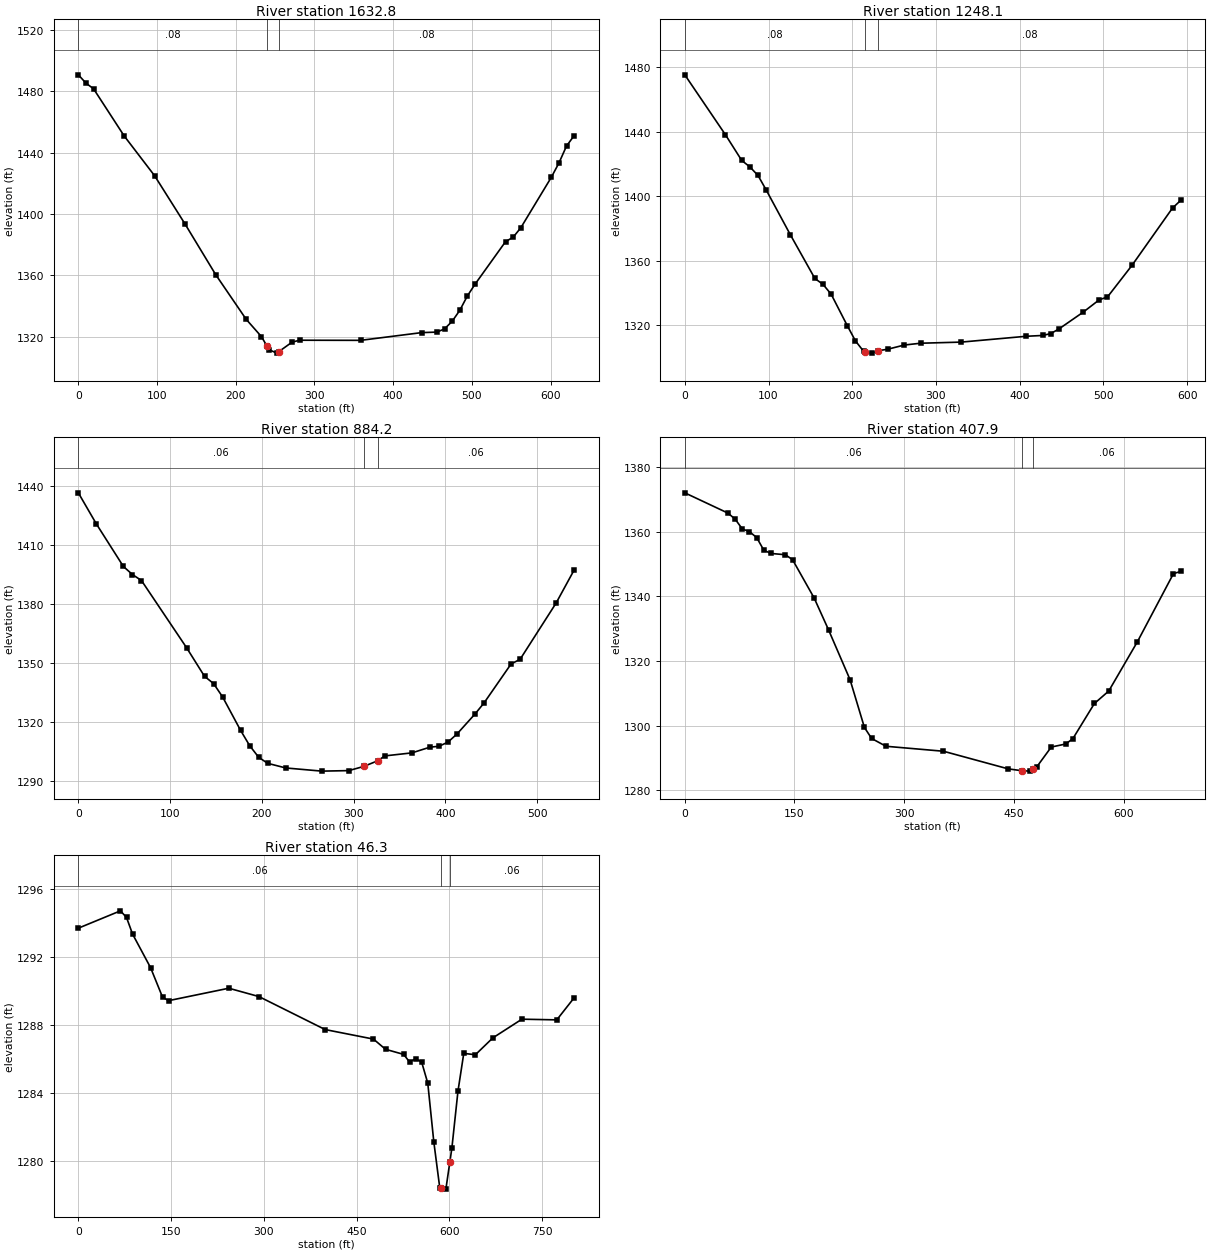
Type RM Length L Ch R = 1 ,1632.8  ,393.2,384.7,376.1
XS GIS Cut Line= 2
     1767033.769      294839.507     1766580.257      295276.696
#Sta/Elev= 30
       0 1490.73     9.7 1485.32    19.4 1481.58    58.2 1450.89    96.9  1424.9
   135.7  1393.3   174.4 1360.46   213.2 1331.26   232.6 1319.96   239.5  1313.9
   242.3 1311.46     252 1309.18   254.5 1310.07   271.4  1316.3     281  1317.6
   358.6 1317.52   436.1 1322.56   455.5  1322.9   465.2 1324.98   474.9 1329.94
   484.6 1337.09   494.2 1346.45   503.9 1354.08   542.7 1381.89   552.4 1384.81
   562.1 1390.93   600.8 1423.82   610.5 1433.16   620.2 1444.28   629.9  1451.1
#Mann= 3 , 0 , 0
       0     .08       0   239.5    .045       0   254.5     .08       0
Bank Sta=239.5,254.5
XS Rating Curve= 0 ,0
Exp/Cntr=0.3,0.1

Type RM Length L Ch R = 1 ,1248.1  ,364.6,363.9,363.2
XS GIS Cut Line= 2
     1766629.008      294599.238     1766385.089      295139.019
#Sta/Elev= 30
       0 1475.27    48.6 1438.06      68 1422.17    77.7 1418.18    87.4 1412.89
    97.1 1403.98   126.2 1375.97   155.4 1348.94   165.1  1345.3   174.8 1339.23
   194.2 1319.59   203.9  1310.2   213.6 1303.78   215.8 1303.53   223.3 1302.65
   230.8 1304.11   242.8 1305.12   262.2 1307.67   281.6 1308.79   330.2 1309.49
   407.8  1313.1   427.3  1313.6     437 1314.74   446.7 1317.57   475.8 1328.02
   495.2 1335.77   504.9 1337.47   534.1 1357.02   582.6 1392.65   592.3 1397.34
#Mann= 3 , 0 , 0
       0     .08       0   215.8    .045       0   230.8     .08       0
Bank Sta=215.8,230.8
XS Rating Curve= 0 ,0
Exp/Cntr=0.3,0.1

Type RM Length L Ch R = 1 ,884.2   ,469,476.3,483.7
XS GIS Cut Line= 2
     1766304.669      294437.068     1766097.385      294936.065
#Sta/Elev= 30
       0  1436.3    19.6 1420.53    49.1 1398.89      59 1394.78    68.8 1391.75
   117.9 1357.66   137.5 1343.09   147.4 1339.38   157.2 1332.63   176.8 1315.63
   186.7 1307.87   196.5 1301.96   206.3 1298.89     226 1296.53   265.3 1294.92
   294.7 1295.18   311.1 1297.32   326.1 1300.15     334 1302.66   363.5 1304.19
   383.2  1307.1     393 1307.54   402.8 1309.67   412.6 1313.77   432.3 1323.96
   442.1 1329.56   471.6 1349.39   481.4 1351.72   520.7 1380.36   540.3 1397.12
#Mann= 3 , 0 , 0
       0     .06       0   311.1    .045       0   326.1     .06       0
Bank Sta=311.1,326.1
XS Rating Curve= 0 ,0
Exp/Cntr=0.3,0.1

Type RM Length L Ch R = 1 ,407.9   ,351.4,361.6,370.5
XS GIS Cut Line= 2
     1766098.392      294111.422     1765652.995      294622.581
#Sta/Elev= 30
       0 1372.09      59 1365.81    68.8 1363.96    78.6 1360.91    88.4 1360.06
    98.3 1358.23   108.1  1354.3   117.9 1353.31   137.6 1352.91   147.4 1351.36
   176.9  1339.5   196.5 1329.68     226 1314.19   245.6 1299.41   255.5 1295.99
   275.1 1293.58   353.7 1292.04   442.2 1286.58   461.4 1285.99   471.6 1285.88
   476.4 1286.55   481.5 1287.26   501.1 1293.34   520.8 1294.28   530.6 1295.92
   560.1 1306.83   579.7 1310.69     619    1326   668.2 1347.06     678 1347.73
#Mann= 3 , 0 , 0
       0     .06       0   461.4    .045       0   476.4     .06       0
Bank Sta=461.4,476.4
XS Rating Curve= 0 ,0
Exp/Cntr=0.3,0.1

Type RM Length L Ch R = 1 ,46.3    ,59.1,46.3,34.8
XS GIS Cut Line= 4
      1765984.58      293927.897     1765693.233       294171.18
     1765481.789      294271.946     1765378.941      294429.256
#Sta/Elev= 30
       0 1293.68    68.1  1294.7    77.9 1294.31    87.6 1293.34   116.8 1291.36
   136.2 1289.62     146 1289.42   243.3 1290.15     292 1289.66   399.1 1287.72
   477.2 1287.16   496.7 1286.56     526 1286.26   535.7 1285.81   545.5 1286.01
   555.2  1285.8     565 1284.57   574.8 1281.11   584.5 1278.39   585.8 1278.38
   594.3 1278.34   600.8 1279.96     604 1280.76   613.8 1284.09   623.2 1286.32
     642 1286.24   670.2 1287.23   717.2 1288.33   773.6 1288.29   801.7 1289.59
#Mann= 3 , 0 , 0
       0     .06       0   585.8    .045       0   600.8     .06       0
Bank Sta=585.8,600.8
XS Rating Curve= 0 ,0
Exp/Cntr=0.3,0.1

Chan Stop Cuts=-1
Use User Specified Reach Order=0
Composite Channel Slope=5